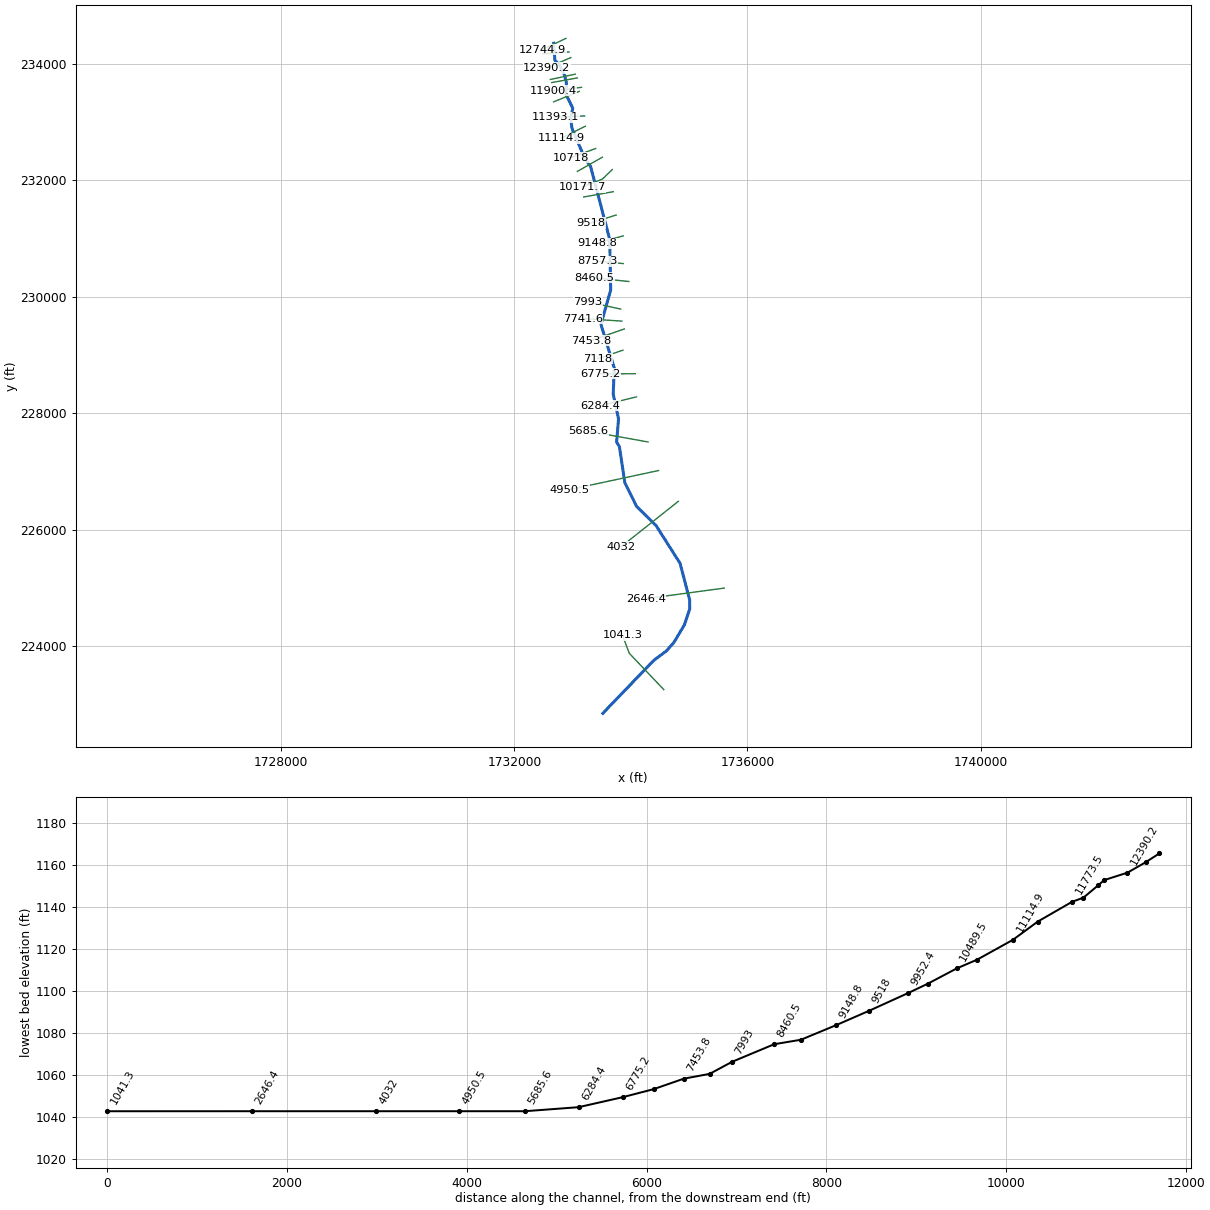
--- lthrwdcrk.prj (project) ---

Proj Title=lthrwdcrk
Current Plan=p01
Default Exp/Contr=0,0
English Units
Geom File=g01
Flow File=f01
Plan File=p01
BEGIN DESCRIPTION:
END DESCRIPTION:
DSS Export Rating Curves= 0
DSS Export Rating Curve Sorted= 0
DSS Export Volume Flow Curves= 0
DXF OffsetX= 0
DXF OffsetY= 0
DXF ScaleX= 0
DXF ScaleY= 0

--- lthrwdcrk.p01 (plan) ---

Plan Title=Approximate Study - 100yr
Program Version=4.00
Geom File=g01
Flow File=f01
Subcritical Flow
K Sum by GR= 0
Std Step Tol= 0.01
Critical Tol= 0.01
Num of Std Step Trials= 20
Max Error Tol= 0.3
Flow Tol Ratio= 0.001
Split Flow NTrial= 30
Split Flow Tol= 0.02
Split Flow Ratio= 0.02
Log Output Level= 0
Friction Slope Method= 1
Unsteady Friction Slope Method= 2
Unsteady Bridges Friction Slope Method= 1
Parabolic Critical Depth
Global Vel Dist= 0 , 0 , 0
Global Log Level= 0
CheckData=True
Encroach Param=-1 ,0,0, 0
Run HTab= 0
Run UNet= 0
Run PostProcess= 0
Run WQNet= 0
UNET Theta= 0
UNET Theta Warmup= 0
UNET ZTol= 0
UNET ZSATol= 0
UNET MxIter= 0
UNET MaxInSteps= 0
UNET DtIC= 0
UNET DtMin= 0
UNET MaxCRTS= 0
UNET WFStab= 0
UNET SFStab= 0
UNET WFX= 1
UNET SFX= 1
UNET DSS MLevel= 1
UNET DZMax Abort= 0
UNET Convert EG Bridges= 0
UNET Use Existing IB Tables= 0
UNET Froude Reduction=False
UNET Froude Limit= 0
UNET Froude Power= 0
UNET Time Slicing=0,0, 5
Write IC File= 0
Echo Input=False
Echo Output=False
Write Detailed= 0
Detailed Automatic Start=False, 0
WQ ULTIMATE=-1
WQ Max Comp Step=1HOUR
WQ Output Interval=15MIN
WQ Output Selected Increments= 0
WQ Output face flow=0
WQ Output face velocity=0
WQ Output face area=0
WQ Output face dispersion=0
WQ Output cell volume=0
WQ Output cell surface area=0
WQ Output cell continuity=0
WQ Output face conc=0
WQ Output face dconc_dx=0
WQ Output face courant=0
WQ Output face peclet=0
WQ Output face adv mass=0
WQ Output face disp mass=0
WQ Output cell mass=0
WQ Output cell source sink temp=0
WQ Output cell source sink nsm=0
WQ Output MaxMinRange=-1
WQ Daily Max Min Mean=-1
WQ Daily Range=0
WQ Daily Time=0
WQ Create Restart=0
WQ Fixed Restart=0
WQ System Summary=False
Sorting and Armoring Iterations= 10
XS Update Threshold= 0.02
Hydraulics Update Threshold= 0.02
Energy Slope Method= 1
Volume Change Method= 0
XS Weighting Method= 0
Number of US Weighted Cross Sections= 1
Number of DS Weighted Cross Sections= 1
Upstream XS Weight=0.25
Main XS Weight=0.5
Downstream XS Weight=0.25
Number of DS XS's Weighted with US Boundary= 1
Upstream Boundary Weight= 1
Weight of XSs Associated with US Boundary= 0
Number of US XS's Weighted with DS Boundary= 1
Downstream Boundary Weight= 0.5
Weight of XSs Associated with DS Boundary= 0.5
Sediment Output Level= 4
Mass or Volume Output= 0
Output Increment Type= 1
Profile and TS Output Increment= 10
XS Output Flag= 0
XS Output Increment= 10
Disregard all LS=0
Disregard all Conn=0
Disregard all Breaches=0
Disregard all Pumps=0

--- lthrwdcrk.f01 (steady flow) ---

Flow Title=USGS Regression Equation
Program Version=4.00
Number of Profiles= 1
Profile Names=P100yr
River Rch & RM=lthrwdcrk,Main            ,12744.9
     437
River Rch & RM=lthrwdcrk,Main            ,12591
     440
River Rch & RM=lthrwdcrk,Main            ,10171.7
     489
River Rch & RM=lthrwdcrk,Main            ,9518
     547
River Rch & RM=lthrwdcrk,Main            ,7741.6
     582
River Rch & RM=lthrwdcrk,Main            ,7453.8
     759
River Rch & RM=lthrwdcrk,Main            ,7118
     761
River Rch & RM=lthrwdcrk,Main            ,6775.2
     848
River Rch & RM=lthrwdcrk,Main            ,4950.5
     943
Boundary for River Rch & Prof#=lthrwdcrk,Main            , 1
Up Type= 0
Dn Type= 3
Dn Slope=0.000001
DSS Import GetInterval= 0
DSS Import GetPeak= 0
DSS Import FillOption= 0

--- lthrwdcrk.g01 (geometry) ---

Geom Title=USGS 3m DEM
Program Version=4.00

River Reach=lthrwdcrk       ,Main
Reach XY= 30
     1732674.473      234353.175     1732695.231      234058.333
     1732764.082      233993.876     1732863.192      233798.763
      1732893.37      233669.817     1732884.017      233478.038
      1733002.19       233236.77     1732966.479      233071.443
      1732988.08      232890.002     1733214.137      232362.003
     1733308.138      232236.405     1733635.828      230983.109
     1733652.543      230113.573     1733485.702      229523.151
     1733715.376      228771.398     1733695.442      228329.857
     1733787.392      227901.134     1733754.207       227504.85
     1733802.909      227422.577     1733895.935      226803.389
      1734096.15      226400.684     1734432.764      226067.244
     1734844.036      225419.875     1735007.422      224795.266
     1735009.569      224639.388     1734917.528      224363.366
     1734737.803      224062.456     1734608.972      223916.335
      1734389.21      223751.823      1733517.15      222844.039

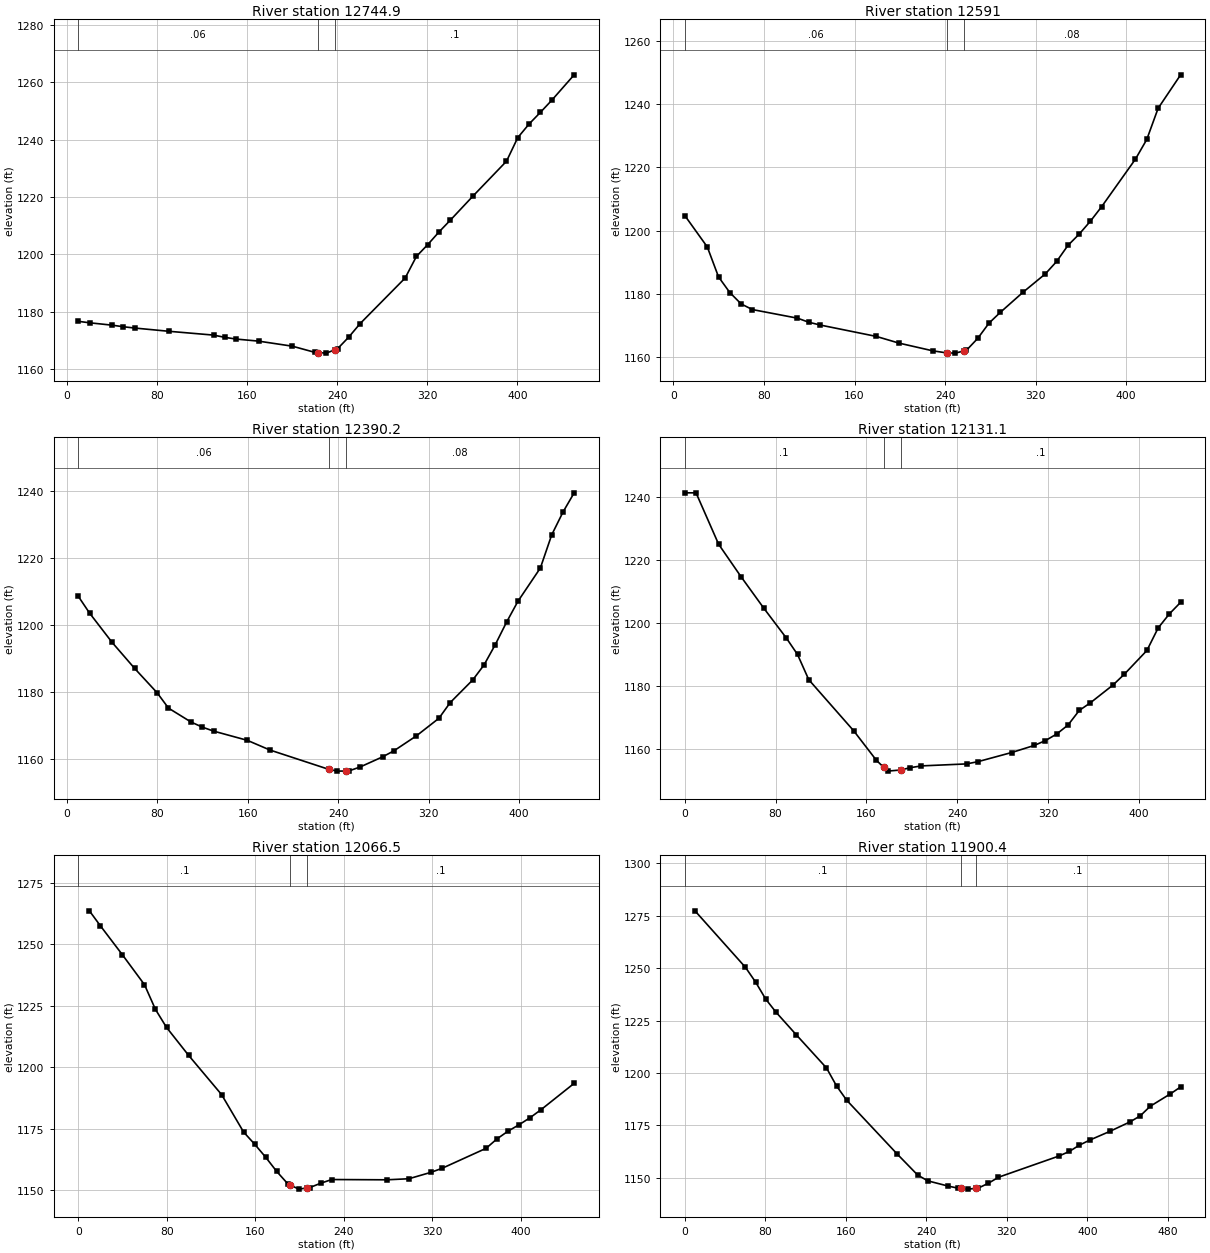
Type RM Length L Ch R = 1 ,12744.9 ,162.4,153.9,145.4
XS GIS Cut Line= 2
     1732885.795      234436.847     1732479.757      234241.957
#Sta/Elev= 30
      10 1176.69      20 1176.18      40 1175.35      50  1174.8    60.1 1174.35
    90.1 1173.23   130.1 1171.89   140.1 1171.11   150.1 1170.51   170.1 1169.79
   200.2 1168.02   220.2 1165.86   222.7  1165.8   230.2 1165.61   237.7 1166.74
   240.2 1167.12   250.2  1171.2   260.2 1175.86   300.3 1191.79   310.3 1199.31
   320.3  1203.4   330.3 1207.81   340.3 1211.89   360.3 1220.24   390.3 1232.48
   400.3 1240.69   410.4 1245.46   420.4  1249.5   430.4 1253.67   450.4 1262.58
#Mann= 3 , 0 , 0
      10     .06       0   222.7    .045       0   237.7      .1       0
Bank Sta=222.7,237.7
XS Rating Curve= 0 ,0
Exp/Cntr=0.3,0.1

Type RM Length L Ch R = 1 ,12591   ,193.6,200.9,207.6
XS GIS Cut Line= 2
     1732938.705      234203.601     1732491.661      234171.858
#Sta/Elev= 30
      10 1204.79    29.9 1194.87    39.8 1185.44    49.8 1180.48    59.8  1176.9
    69.7 1175.12   109.6  1172.4   119.5 1171.13   129.5 1170.25   179.3 1166.64
   199.2 1164.54   229.1  1162.1   241.5 1161.44     249 1161.37   256.5 1162.04
   258.9 1162.26   268.9 1166.03   278.9 1170.86   288.8 1174.22   308.7 1180.52
   328.7  1186.4   338.6 1190.29   348.6 1195.36   358.5 1198.91   368.5 1203.02
   378.5 1207.64   408.3 1222.61   418.3 1228.81   428.3 1238.63   448.2  1249.2
#Mann= 3 , 0 , 0
      10     .06       0   241.5    .045       0   256.5     .08       0
Bank Sta=241.5,256.5
XS Rating Curve= 0 ,0
Exp/Cntr=0.3,0.1

Type RM Length L Ch R = 1 ,12390.2 ,263.1,259,255.5
XS GIS Cut Line= 2
     1732969.125       234107.05     1732557.792      233927.175
#Sta/Elev= 30
      10 1208.61      20 1203.59    39.9 1194.87    59.9 1187.08    79.8 1179.81
    89.8 1175.25   109.7 1171.11   119.7 1169.58   129.7 1168.39   159.6 1165.63
   179.6 1162.74   231.9 1156.95   239.4 1156.44   246.9 1156.48   249.4 1156.49
   259.4 1157.67   279.3  1160.7   289.3 1162.49   309.3 1166.98   329.2 1172.22
   339.2 1176.91   359.2 1183.69   369.1 1188.13   379.1 1194.21   389.1 1200.94
   399.1 1207.12     419 1217.09     429 1226.95     439 1233.77   448.9 1239.52
#Mann= 3 , 0 , 0
      10     .06       0   231.9    .045       0   246.9     .08       0
Bank Sta=231.9,246.9
XS Rating Curve= 0 ,0
Exp/Cntr=0.3,0.1

Type RM Length L Ch R = 1 ,12131.1 ,65.3,64.6,63.9
XS GIS Cut Line= 2
     1733044.514      233821.365     1732617.309      233730.105
#Sta/Elev= 30
       0 1241.19     9.9 1241.19    29.8 1224.88    49.6 1214.55    69.5 1204.64
    89.4 1195.15    99.3 1189.91   109.2 1181.91   148.9 1165.65   168.8 1156.33
   175.21154.113   178.7  1152.9   190.21153.268   198.6 1153.99   208.5 1154.56
   248.2 1155.19   258.1 1155.89   287.9  1158.8   307.8 1161.04   317.7 1162.59
   327.6 1164.67   337.6 1167.52   347.5 1172.15   357.4  1174.6   377.3 1180.24
   387.2 1183.64   407.1 1191.18     417 1198.32   426.9 1202.79   436.8 1206.45
#Mann= 3 , 0 , 0
       0      .1       0   175.2    .045       0   190.2      .1       0
Bank Sta=175.2,190.2
XS Rating Curve= 0 ,0
Exp/Cntr=0.3,0.1

Type RM Length L Ch R = 1 ,12066.5 ,168,166.1,164.2
XS GIS Cut Line= 2
     1733081.365      233757.265     1732640.341      233677.161
#Sta/Elev= 30
      10 1263.61    19.9 1257.54    39.8 1245.77    59.8 1233.59    69.7 1223.55
    79.7 1216.24    99.6 1204.91   129.5 1188.91   149.4 1173.69   159.4 1168.75
   169.3 1163.49   179.3 1157.69   189.3 1152.67   191.7 1152.14   199.2 1150.49
   206.7 1150.96   209.2 1151.12   219.1 1152.89   229.1 1154.39   278.9 1154.28
   298.8 1154.71   318.7 1157.31   328.7 1158.93   368.6 1167.08   378.5 1170.93
   388.5 1174.07   398.4 1176.66   408.4 1179.54   418.4 1182.83   448.2 1193.49
#Mann= 3 , 0 , 0
       0      .1       0   191.7    .045       0   206.7      .1       0
Bank Sta=191.7,206.7
XS Rating Curve= 0 ,0
Exp/Cntr=0.3,0.1

Type RM Length L Ch R = 1 ,11900.4 ,121,126.9,132.9
XS GIS Cut Line= 2
     1733152.753      233595.319      1732663.68      233535.753
#Sta/Elev= 30
    10.1 1277.35    60.3 1250.37    70.4 1243.31    80.4 1235.23    90.5 1229.05
   110.6 1218.28   140.8 1202.37   150.8 1193.77   160.9 1186.95   211.2 1161.22
   231.3 1151.31   241.3 1148.51   261.4 1146.03   271.5 1144.99     274 1144.88
   281.5 1144.54     289 1144.89   291.6 1145.02   301.6 1147.33   311.7 1150.21
     372 1160.37   382.1 1162.53   392.1 1165.52   402.2  1167.9   422.3 1172.09
   442.4 1176.63   452.5 1179.48   462.5 1184.09   482.6 1190.02   492.7 1193.32
#Mann= 3 , 0 , 0
       0      .1       0     274    .045       0     289      .1       0
Bank Sta=274,289
XS Rating Curve= 0 ,0
Exp/Cntr=0.3,0.1

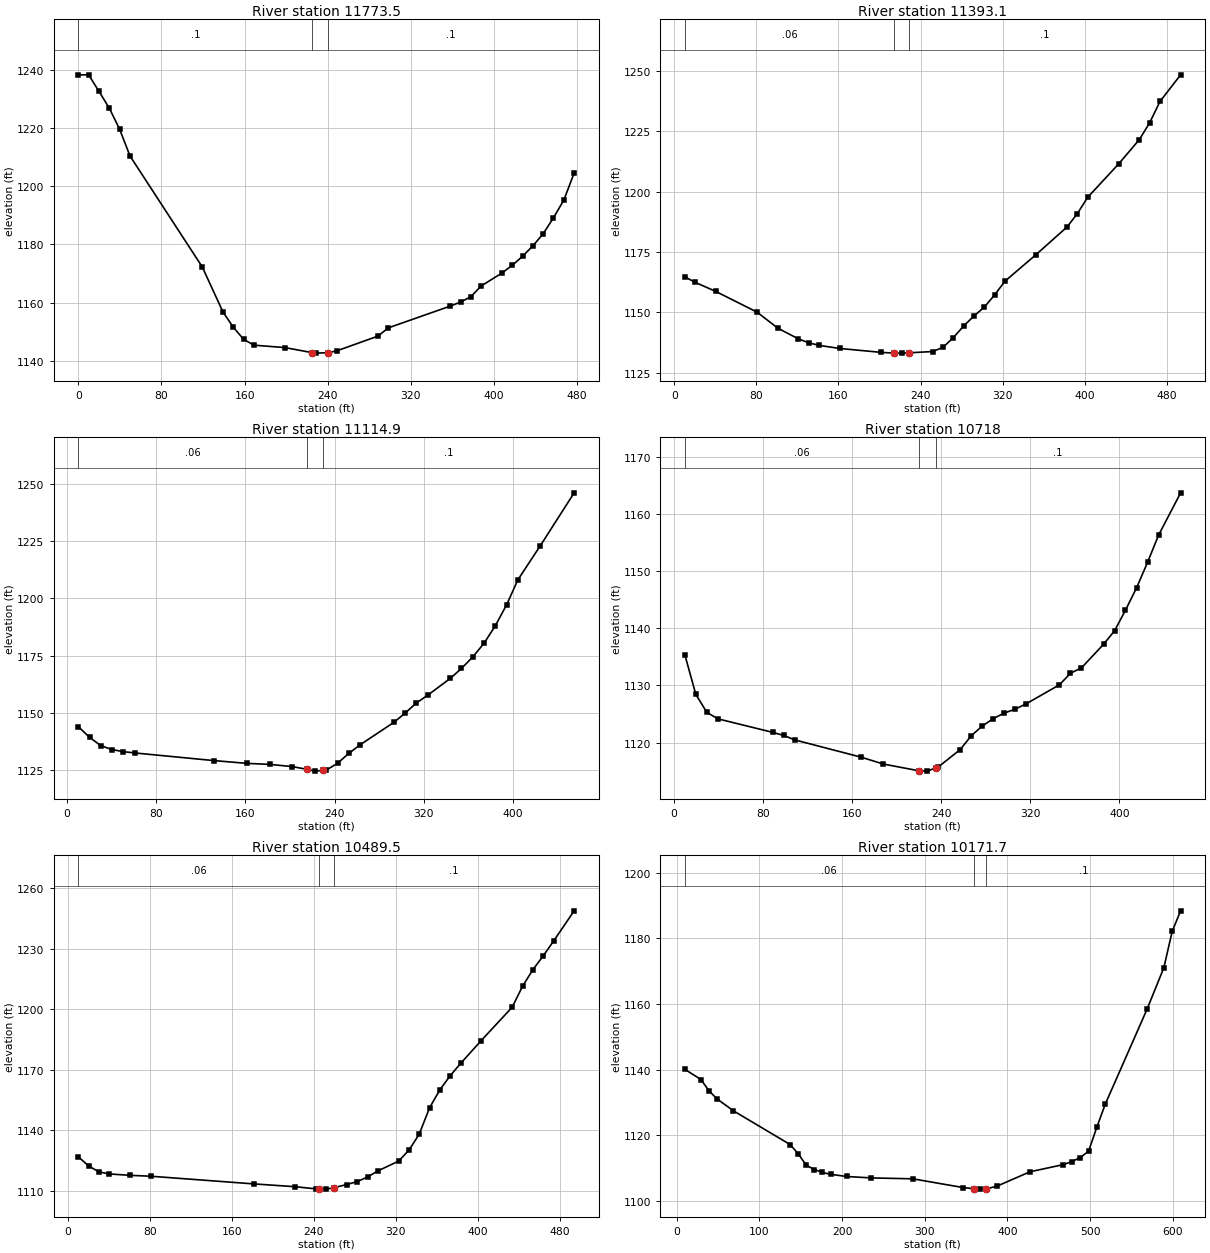
Type RM Length L Ch R = 1 ,11773.5 ,387.7,380.4,373.4
XS GIS Cut Line= 2
     1733114.612      233526.422     1732673.055      233345.714
#Sta/Elev= 30
       0 1238.49     9.9 1238.49    19.9 1232.78    29.8    1227    39.8 1219.69
    49.7 1210.52   119.3 1172.23   139.2 1156.71   149.1  1151.5     159 1147.31
     169 1145.29   198.8 1144.46   225.11142.713   228.6 1142.55   240.11142.699
   248.5 1143.31   288.3 1148.42   298.2 1151.25   357.8 1158.75   367.8 1160.15
   377.7 1162.01   387.6 1165.69   407.5 1170.14   417.5 1172.81   427.4 1175.92
   437.3  1179.5   447.3 1183.71   457.2 1189.19   467.2 1195.35   477.1 1204.63
#Mann= 3 , 0 , 0
       0      .1       0   225.1    .045       0   240.1      .1       0
Bank Sta=225.1,240.1
XS Rating Curve= 0 ,0
Exp/Cntr=0.3,0.1

Type RM Length L Ch R = 1 ,11393.1 ,269,278.2,287
XS GIS Cut Line= 2
      1733206.02      233104.312     1732712.778      233082.261
#Sta/Elev= 30
    10.1 1164.73    20.2 1162.47    40.3  1158.7    80.6 1150.12   100.8  1143.5
   120.9 1139.05     131 1137.44   141.1 1136.37   161.2 1135.09   201.5 1133.48
   214.2 1133.17   221.7 1133.16   229.2  1133.3   251.9 1133.82     262 1135.58
   272.1 1139.61   282.1  1144.4   292.2 1148.56   302.3 1152.21   312.4 1157.34
   322.4 1162.95   352.7 1173.95   382.9 1185.38     393 1190.93     403 1197.64
   433.3 1211.51   453.4 1221.54   463.5 1228.52   473.6 1237.37   493.7 1248.37
#Mann= 3 , 0 , 0
    10.1     .06       0   214.2    .045       0   229.2      .1       0
Bank Sta=214.2,229.2
XS Rating Curve= 0 ,0
Exp/Cntr=0.3,0.1

Type RM Length L Ch R = 1 ,11114.9 ,399.3,396.9,394.5
XS GIS Cut Line= 2
     1733215.994      232926.562     1732809.149      232722.748
#Sta/Elev= 30
    10.1 1143.87    20.2  1139.2    30.3 1135.57    40.4 1133.84    50.6 1132.94
    60.7 1132.38   131.5 1129.04   161.8  1127.8     182 1127.37   202.2 1126.39
     215 1125.24   222.5 1124.42     230 1124.76   232.6 1124.88   242.7 1127.86
   252.8 1132.19   262.9 1135.93   293.2 1145.75   303.4 1149.84   313.5 1154.29
   323.6 1157.64   343.8 1164.99   353.9 1169.36     364 1174.39   374.1 1180.36
   384.3 1188.08   394.4 1197.23   404.5 1208.16   424.7 1223.13     455 1246.23
#Mann= 3 , 0 , 0
    10.1     .06       0     215    .045       0     230      .1       0
Bank Sta=215,230
XS Rating Curve= 0 ,0
Exp/Cntr=0.3,0.1

Type RM Length L Ch R = 1 ,10718   ,224.9,228.5,232
XS GIS Cut Line= 3
     1733394.748      232545.258      1733181.59      232465.759
     1732968.595      232385.824
#Sta/Elev= 30
     9.9 1135.38    19.8 1128.42    29.7 1125.29    39.6 1124.15      89 1121.78
    98.9 1121.24   108.8 1120.46   168.2 1117.45   187.9 1116.26     220 1115.07
   227.5 1115.01     235 1115.56   237.4 1115.73   257.2 1118.79   267.1 1121.21
     277  1122.9   286.8 1124.19   296.7 1125.17   306.6 1125.85   316.5  1126.8
   346.2  1130.1   356.1 1132.12     366 1133.07   385.8 1137.18   395.7 1139.56
   405.5 1143.15   415.4 1147.04   425.3 1151.51   435.2 1156.27     455 1163.67
#Mann= 3 , 0 , 0
     9.9     .06       0     220    .045       0     235      .1       0
Bank Sta=220,235
XS Rating Curve= 0 ,0
Exp/Cntr=0.3,0.1

Type RM Length L Ch R = 1 ,10489.5 ,320.9,317.8,314.6
XS GIS Cut Line= 2
     1733510.123      232395.783     1733080.616      232151.246
#Sta/Elev= 30
    10.1 1126.83    20.2 1122.25    30.3 1119.36    40.3 1118.33    60.5 1117.64
    80.7  1117.2   181.6 1113.38   221.9    1112   242.1 1110.92   244.7 1110.89
   252.2  1110.8   259.7 1111.53   272.3 1113.09   282.4 1114.53   292.5 1116.83
   302.6 1119.84   322.8  1124.7   332.9 1130.11   342.9 1138.02     353  1151.1
   363.1 1160.07   373.2 1167.04   383.3  1173.1   403.5 1184.48   433.7 1201.01
   443.8 1211.38   453.9 1219.62     464 1226.45   474.1  1233.8   494.2 1248.79
#Mann= 3 , 0 , 0
    10.1     .06       0   244.7    .045       0   259.7      .1       0
Bank Sta=244.7,259.7
XS Rating Curve= 0 ,0
Exp/Cntr=0.3,0.1

Type RM Length L Ch R = 1 ,10171.7 ,223.8,219.3,214.8
XS GIS Cut Line= 3
     1733679.418      232182.597     1733510.123      232019.573
     1733162.129      231881.629
#Sta/Elev= 30
     9.8 1140.12    29.4 1136.98    39.2  1133.5      49 1131.06    68.5 1127.48
   137.1  1117.2   146.9 1114.39   156.7 1110.88   166.5 1109.58   176.3 1108.67
   186.1 1108.11   205.6 1107.45     235 1107.02   285.6 1106.74   346.3 1104.08
   359.1 1103.74   366.6  1103.6   374.1 1103.68   386.8 1104.45   427.3 1108.89
   467.7 1111.08   477.8 1111.99     488 1113.21   498.1 1115.16   508.2 1122.57
   518.3 1129.52   568.9 1158.49   589.1 1171.07   599.2 1182.15   609.4 1188.41
#Mann= 3 , 0 , 0
     9.8     .06       0   359.1    .045       0   374.1      .1       0
Bank Sta=359.1,374.1
XS Rating Curve= 0 ,0
Exp/Cntr=0.3,0.1

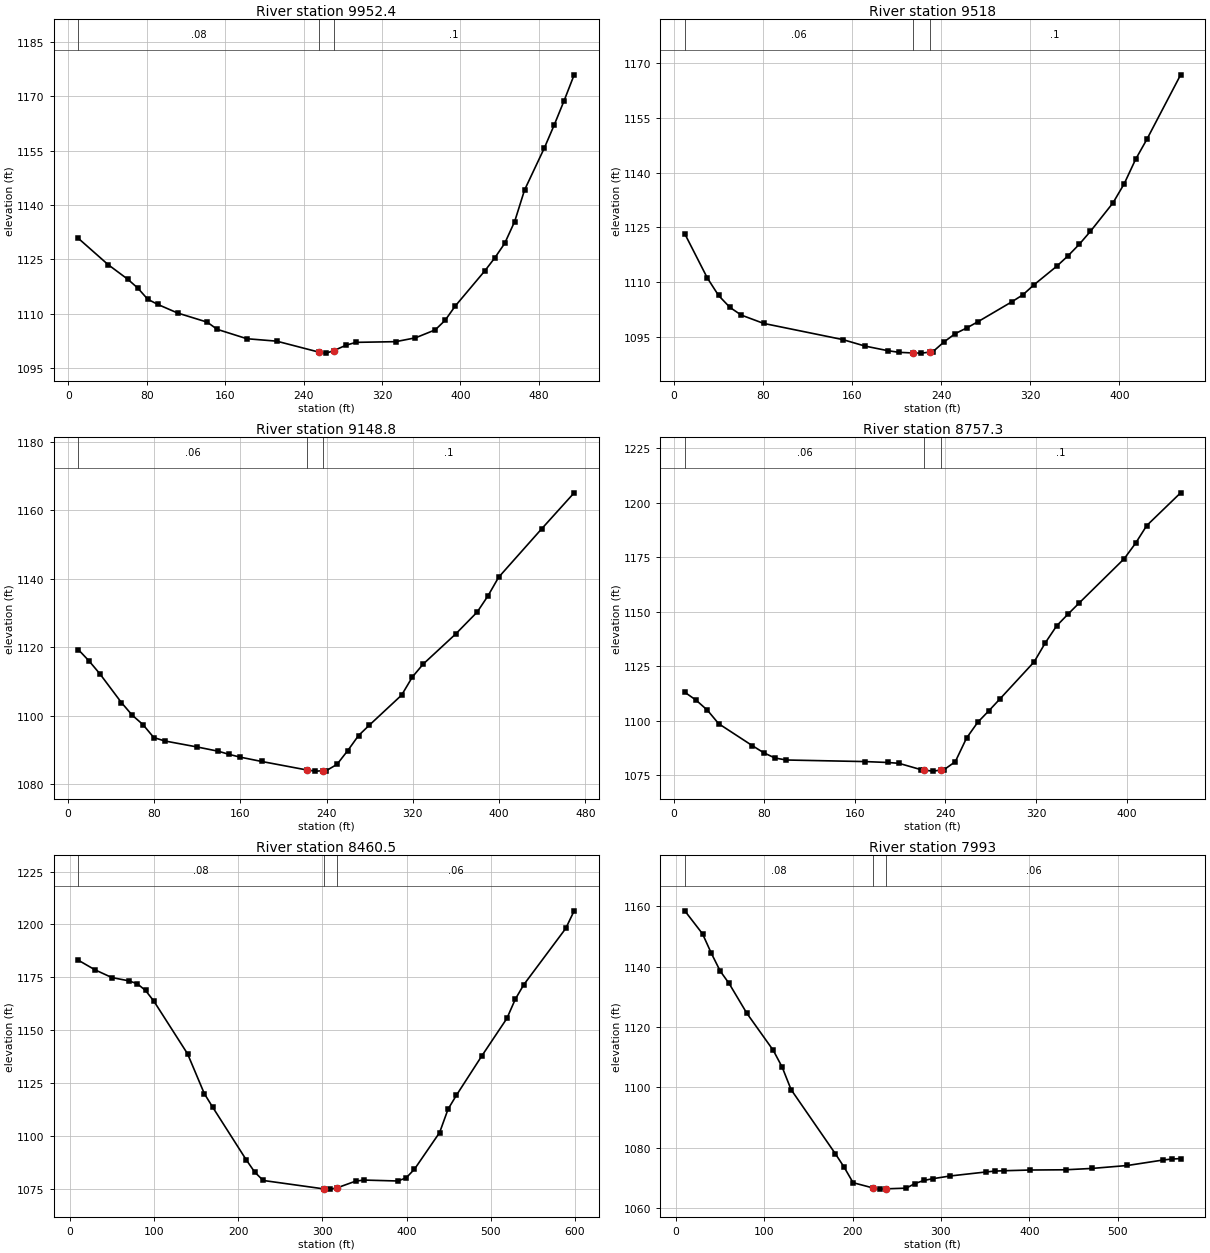
Type RM Length L Ch R = 1 ,9952.4  ,431.5,434.4,437.4
XS GIS Cut Line= 2
     1733698.228      231803.251     1733190.344      231712.334
#Sta/Elev= 30
    10.1 1130.78    40.5 1123.53    60.7 1119.47    70.8 1117.06    80.9 1113.99
    91.1 1112.57   111.3  1110.2   141.6 1107.67   151.8 1105.69   182.1  1103.1
   212.5 1102.43   255.5 1099.41     263 1099.13   270.5 1099.79   283.3 1101.32
   293.4  1102.1   333.9 1102.29   354.1 1103.35   374.3 1105.55   384.4  1108.2
   394.6 1112.09   424.9 1121.83     435 1125.39   445.1 1129.38   455.3 1135.42
   465.4 1144.12   485.6 1155.71   495.7 1162.08   505.8 1168.78     516 1175.87
#Mann= 3 , 0 , 0
    10.1     .08       0   255.5    .045       0   270.5      .1       0
Bank Sta=255.5,270.5
XS Rating Curve= 0 ,0
Exp/Cntr=0.3,0.1

Type RM Length L Ch R = 1 ,9518    ,370,369.2,368.4
XS GIS Cut Line= 2
     1733746.572      231402.302     1733312.882      231264.685
#Sta/Elev= 30
    10.1 1123.26    30.3 1111.21    40.4 1106.42    50.6 1103.17    60.7 1101.08
    80.9 1098.79   151.7 1094.39   171.9  1092.6   192.1 1091.36   202.2  1090.9
   214.9 1090.72   222.4 1090.68   229.9 1090.95   232.6 1091.04   242.7 1093.74
   252.8 1096.01   262.9 1097.53     273 1099.23   303.3 1104.65   313.4 1106.59
   323.6 1109.38   343.8  1114.4   353.9 1117.23     364 1120.38   374.1 1123.95
   394.3  1131.7   404.4 1136.95   414.6  1143.6   424.7 1149.06     455 1166.68
#Mann= 3 , 0 , 0
    10.1     .06       0   214.9    .045       0   229.9      .1       0
Bank Sta=214.9,229.9
XS Rating Curve= 0 ,0
Exp/Cntr=0.3,0.1

Type RM Length L Ch R = 1 ,9148.8  ,399.7,391.5,383.3
XS GIS Cut Line= 2
     1733867.523      231044.561     1733415.272      230918.598
#Sta/Elev= 30
      10  1119.3      20 1115.97      30 1112.21    49.9 1103.84    59.9 1100.15
    69.9 1097.39    79.9 1093.61    89.9 1092.62   119.9 1090.86   139.8  1089.6
   149.8 1088.68   159.8 1087.89   179.8 1086.62   222.2  1084.1   229.7 1083.79
   237.2 1083.88   239.7 1083.91   249.7 1085.76   259.7  1089.8   269.7  1094.2
   279.7 1097.23   309.6 1106.01   319.6 1111.32   329.6 1115.08   359.6 1123.84
   379.6 1130.27   389.6    1135   399.5 1140.45   439.5 1154.65   469.5 1165.13
#Mann= 3 , 0 , 0
      10     .06       0   222.2    .045       0   237.2      .1       0
Bank Sta=222.2,237.2
XS Rating Curve= 0 ,0
Exp/Cntr=0.3,0.1

Type RM Length L Ch R = 1 ,8757.3  ,297.2,296.8,296.5
XS GIS Cut Line= 2
      1733868.13      230568.785     1733422.341      230608.784
#Sta/Elev= 30
     9.9 1113.04    19.9  1109.4    29.8 1104.84    39.8 1098.61    69.6  1088.5
    79.6 1085.26    89.5 1082.86    99.5 1081.95   169.1 1081.22     189 1080.81
   198.9 1080.43   218.8 1077.46   221.3  1077.3   228.8 1076.84   236.3 1077.33
   238.7 1077.49   248.7 1081.18   258.6    1092   268.5 1099.26   278.5 1104.64
   288.4 1110.15   318.3    1127   328.2 1135.78   338.2 1143.55   348.1 1148.86
   358.1 1154.05   397.8 1174.34   407.8 1181.43   417.7 1189.57   447.6 1204.59
#Mann= 3 , 0 , 0
     9.9     .06       0   221.3    .045       0   236.3      .1       0
Bank Sta=221.3,236.3
XS Rating Curve= 0 ,0
Exp/Cntr=0.3,0.1

Type RM Length L Ch R = 1 ,8460.5  ,469.9,467.4,465
XS GIS Cut Line= 2
     1733964.711      230260.789     1733369.044      230323.491
#Sta/Elev= 30
      10 1183.06    29.9 1178.49    49.9 1174.85    69.9 1173.31    79.9 1171.95
    89.8 1168.76    99.8 1163.65   139.8 1138.73   159.7 1119.89   169.7 1113.44
   209.6  1088.5   219.6 1082.75   229.6 1078.82     302 1074.81   309.5 1074.72
     317 1075.27   339.4  1078.5   349.4 1079.01   389.3 1078.57   399.3    1080
   409.3 1084.15   439.2 1101.52   449.2 1112.57   459.2  1119.2   489.1 1137.65
   519.1 1155.53   529.1 1164.63   539.1 1171.45     589 1198.11     599 1206.44
#Mann= 3 , 0 , 0
      10     .08       0     302    .045       0     317     .06       0
Bank Sta=302,317
XS Rating Curve= 0 ,0
Exp/Cntr=0.3,0.1

Type RM Length L Ch R = 1 ,7993    ,247.9,251.4,255
XS GIS Cut Line= 2
     1733823.632      229787.391     1733265.586      229909.659
#Sta/Elev= 30
      10 1158.42    30.1  1150.8    40.1 1144.34    50.1 1138.49    60.1 1134.41
    80.2 1124.55   110.2 1112.25   120.3 1106.67   130.3 1099.29   180.4 1078.08
   190.4 1073.61   200.5 1068.49     223 1066.75   230.5 1066.36     238 1066.46
   260.6 1066.68   270.6 1068.21   280.6 1069.23   290.7 1069.81   310.7 1070.72
   350.8 1072.03   360.8 1072.32   370.8 1072.44   400.9 1072.68     441 1072.76
   471.1 1073.21   511.1 1074.18   551.2 1075.98   561.3 1076.31   571.3 1076.47
#Mann= 3 , 0 , 0
      10     .08       0     223    .045       0     238     .06       0
Bank Sta=223,238
XS Rating Curve= 0 ,0
Exp/Cntr=0.3,0.1

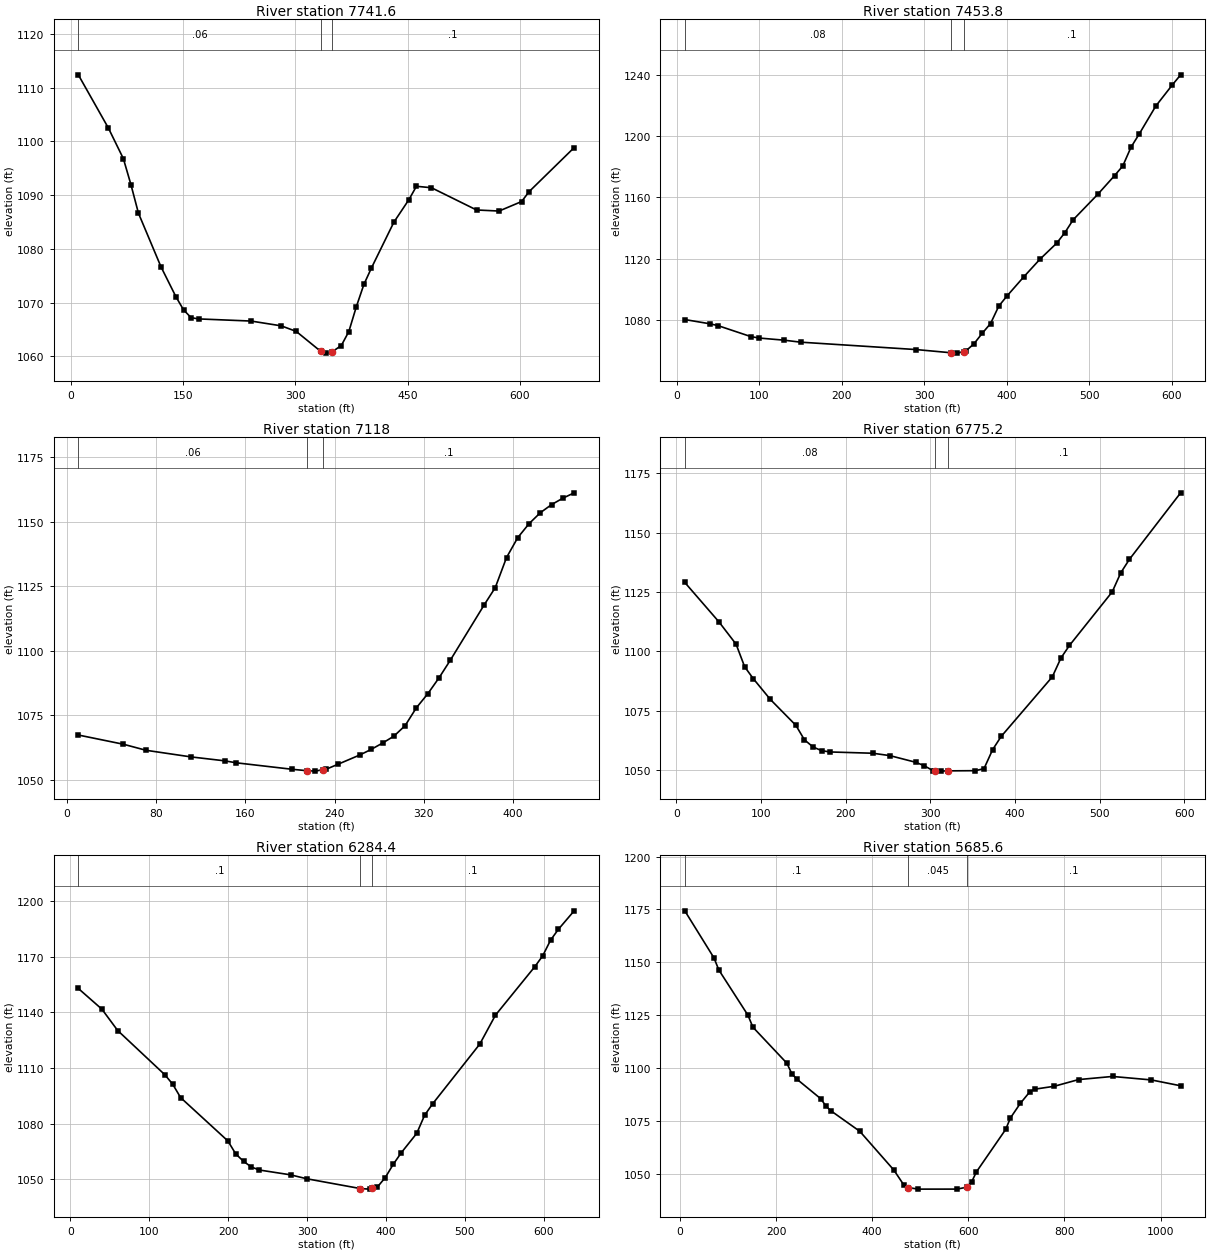
Type RM Length L Ch R = 1 ,7741.6  ,278.5,287.8,297
XS GIS Cut Line= 2
     1733845.577      229580.475     1733174.669      229624.367
#Sta/Elev= 30
      10 1112.39    50.2 1102.47    70.2 1096.77    80.3 1091.93    90.3 1086.63
   120.4 1076.65   140.5 1071.04   150.5 1068.65   160.6 1067.18   170.6 1066.95
   240.8 1066.55     281 1065.66     301 1064.63   333.7 1060.92   341.2 1060.58
   348.7 1060.79   361.3    1062   371.3 1064.59   381.3  1069.2   391.4 1073.36
   401.4  1076.4   431.5 1084.96   451.6 1089.16   461.6 1091.64   481.7 1091.37
   541.9 1087.23     572 1087.03   602.1  1088.8   612.1 1090.64   672.3 1098.84
#Mann= 3 , 0 , 0
      10     .06       0   333.7    .045       0   348.7      .1       0
Bank Sta=333.7,348.7
XS Rating Curve= 0 ,0
Exp/Cntr=0.3,0.1

Type RM Length L Ch R = 1 ,7453.8  ,336.1,335.8,335.6
XS GIS Cut Line= 2
     1733886.333      229445.667     1733309.477      229245.021
#Sta/Elev= 30
      10 1080.21      40 1077.48    50.1 1076.27    90.1 1069.07   100.1 1068.14
   130.2 1066.75   150.2 1065.45   290.4 1060.61   332.9 1058.51   340.4 1058.29
   347.9 1059.31   350.4 1059.64   360.4 1064.38   370.5  1071.3   380.5 1077.61
   390.5 1089.03   400.5 1095.65   420.5 1107.94   440.5 1119.68   460.6 1130.06
   470.6    1137   480.6 1145.35   510.6 1162.08   530.7 1174.14   540.7 1180.47
   550.7 1192.73   560.7 1201.42   580.7 1219.57   600.7 1233.35   610.8 1239.97
#Mann= 3 , 0 , 0
      10     .08       0   332.9    .045       0   347.9      .1       0
Bank Sta=332.9,347.9
XS Rating Curve= 0 ,0
Exp/Cntr=0.3,0.1

Type RM Length L Ch R = 1 ,7118    ,350,342.8,335.6
XS GIS Cut Line= 2
     1733862.441      229080.904     1733431.135      228935.989
#Sta/Elev= 30
    10.1 1067.28    50.6  1063.7    70.8 1061.37   111.2  1058.8   141.6 1057.27
   151.7 1056.52   202.2 1053.99   214.9 1053.47   222.4 1053.29   229.9 1053.85
   232.6 1054.05   242.7 1055.88   262.9 1059.59     273 1061.74   283.1 1064.17
   293.2 1066.82   303.3  1070.9   313.4 1077.82   323.6 1083.23   333.7 1089.41
   343.8 1096.21   374.1 1117.59   384.2 1124.39   394.3 1136.03   404.4 1143.77
   414.6  1149.2   424.7 1153.43   434.8 1156.58   444.9 1159.05     455 1161.12
#Mann= 3 , 0 , 0
    10.1     .06       0   214.9    .045       0   229.9      .1       0
Bank Sta=214.9,229.9
XS Rating Curve= 0 ,0
Exp/Cntr=0.3,0.1

Type RM Length L Ch R = 1 ,6775.2  ,485.5,490.8,496
XS GIS Cut Line= 2
     1734074.439       228677.57     1733478.772      228674.435
#Sta/Elev= 30
    10.1 1129.03    50.5 1112.38    70.7 1102.98    80.8 1093.47    90.9 1088.51
   111.1 1079.73   141.3 1068.79   151.4 1062.69   161.5 1059.69   171.6 1058.12
   181.7 1057.57   232.2 1057.03   252.4 1056.02   282.7 1053.23   292.8 1051.79
   302.9 1049.75   305.5 1049.68     313 1049.49   320.5  1049.6   353.4 1049.68
   363.5 1050.55   373.6  1058.5   383.7 1064.09   444.2 1089.26   454.3 1097.14
   464.4 1102.48   514.9 1125.06     525 1133.09   535.1 1138.72   595.7 1166.81
#Mann= 3 , 0 , 0
    10.1     .08       0   305.5    .045       0   320.5      .1       0
Bank Sta=305.5,320.5
XS Rating Curve= 0 ,0
Exp/Cntr=0.3,0.1

Type RM Length L Ch R = 1 ,6284.4  ,608.3,598.8,589.4
XS GIS Cut Line= 2
     1734096.384      228279.415     1733475.637      228128.931
#Sta/Elev= 30
      10 1152.82    39.9 1141.67    59.9 1130.18   119.8  1106.3   129.7 1101.23
   139.7 1094.03   199.6 1070.69   209.6 1063.69   219.6 1059.64   229.5 1056.63
   239.5 1055.02   279.4  1052.4   299.4 1050.32   367.71045.018   379.2 1044.72
   382.71045.116   389.2 1045.85   399.2 1050.96   409.2 1058.01   419.2 1064.17
   439.1 1074.78   449.1 1084.53   459.1  1090.6     519 1122.84   538.9 1138.44
   588.8 1164.56   598.8 1170.41   608.8 1178.87   618.8 1184.76   638.7 1194.66
#Mann= 3 , 0 , 0
      10      .1       0   367.7    .045       0   382.7      .1       0
Bank Sta=367.7,382.7
XS Rating Curve= 0 ,0
Exp/Cntr=0.3,0.1

Type RM Length L Ch R = 1 ,5685.6  ,726.2,735.1,744
XS GIS Cut Line= 2
     1734293.895      227505.048     1733268.721      227690.018
#Sta/Elev= 30
    10.1 1174.35    70.8  1152.1    80.9  1146.4   141.6 1124.97   151.7 1119.37
   222.5 1102.31   232.6 1097.43   242.7 1094.89   293.3 1085.46   303.4 1082.13
   313.5 1079.92   374.2 1070.13     445 1051.83   465.2 1044.97   475.4 1043.53
   495.6  1042.8   576.5 1042.81   596.7 1043.71   606.8 1046.17   616.9 1050.98
   677.6 1070.99   687.7 1076.48     708 1083.28   728.2 1088.87   738.3 1090.05
   778.8 1091.42   829.3 1094.58   900.1 1096.06     981 1094.41  1041.7 1091.65
#Mann= 3 , 0 , 0
    10.1      .1       0   475.4    .045       0   596.7      .1       0
Bank Sta=475.4,596.7
XS Rating Curve= 0 ,0
Exp/Cntr=0.3,0.1

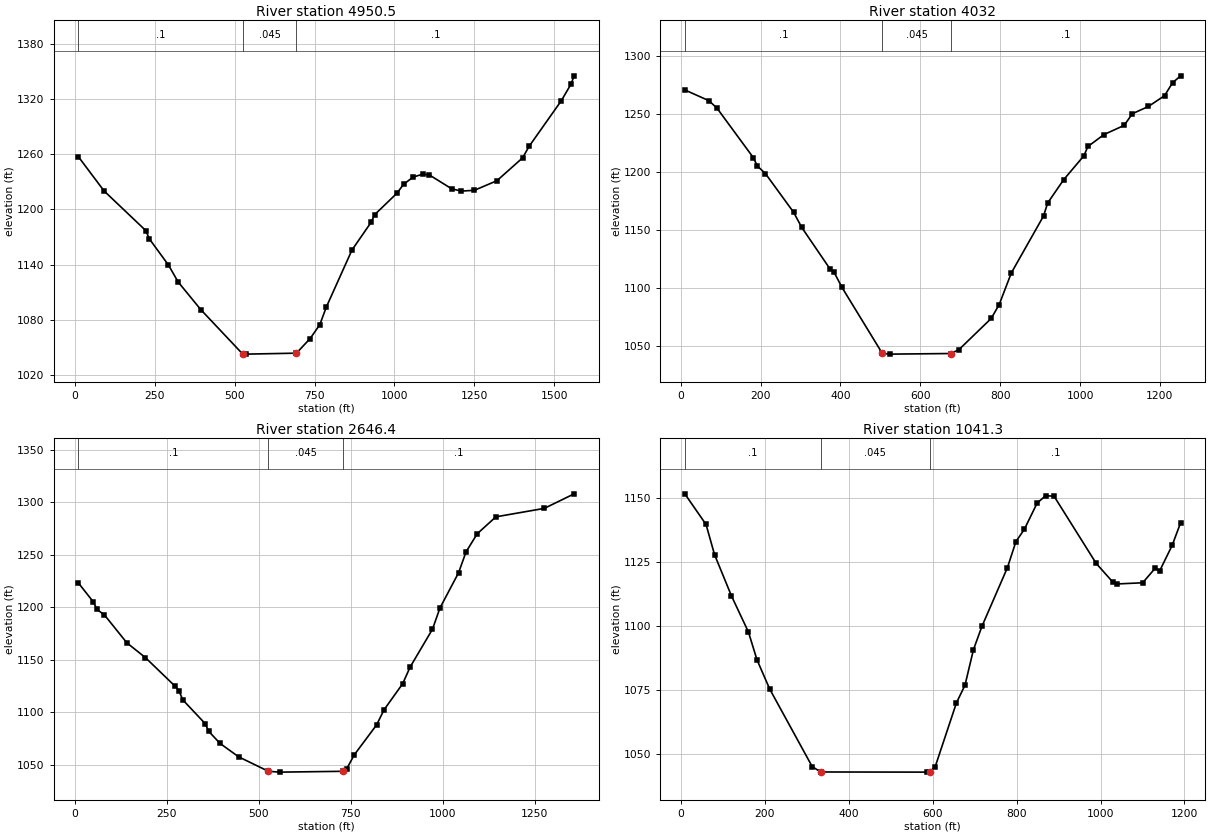
Type RM Length L Ch R = 1 ,4950.5  ,908.1,918.5,928.9
XS GIS Cut Line= 2
     1734473.803      227014.306     1732945.847      226687.135
#Sta/Elev= 30
    10.1 1257.34    90.7 1220.08   221.8 1176.86   231.9 1168.28   292.4 1139.53
   322.6 1121.22   393.2 1091.28   524.2 1043.09   534.3  1042.8     693 1043.84
   735.9 1059.74   766.2 1074.75   786.3 1093.71     867 1155.97   927.5 1186.34
   937.6 1194.19  1008.1 1217.74  1028.3 1227.24  1058.5 1235.17  1088.8 1238.29
  1108.9 1237.53  1179.5 1222.33  1209.7 1219.92  1250.1 1220.77  1320.6 1231.15
  1401.3 1256.07  1421.5 1268.53  1522.3 1318.07  1552.5    1336  1562.6 1345.14
#Mann= 3 , 0 , 0
    10.1      .1       0   524.2    .045       0     693      .1       0
Bank Sta=524.2,693
XS Rating Curve= 0 ,0
Exp/Cntr=0.3,0.1

Type RM Length L Ch R = 1 ,4032    ,1397.7,1385.6,1373.5
XS GIS Cut Line= 2
     1734814.319      226486.145     1733833.821       225707.86
#Sta/Elev= 30
    10.1 1270.61    70.7 1261.27    90.9  1254.8   181.7 1212.21   191.8 1204.98
     212 1198.48   282.7 1165.05   302.9 1152.07   373.5 1116.37   383.6 1113.63
   403.8 1100.27   504.8 1043.39     525  1042.8   676.4 1043.33   696.6 1046.67
   777.4 1073.56   797.5 1085.57   827.8 1112.81   908.6 1161.96   918.7 1173.04
   959.1 1193.28  1009.5  1213.8  1019.6 1221.82    1060 1232.14  1110.5 1240.02
  1130.7 1250.04  1171.1 1256.33  1211.5 1265.62  1231.6 1276.77  1251.8 1282.75
#Mann= 3 , 0 , 0
    10.1      .1       0   504.8    .045       0   676.4      .1       0
Bank Sta=504.8,676.4
XS Rating Curve= 0 ,0
Exp/Cntr=0.3,0.1

Type RM Length L Ch R = 1 ,2646.4  ,1626.4,1605.1,1583.7
XS GIS Cut Line= 2
     1735602.009      224995.412     1734257.057       224814.36
#Sta/Elev= 30
    10.1 1223.19    50.6 1205.14    60.8 1197.82      81 1192.65   141.8 1166.09
   192.4 1151.92   273.4 1124.55   283.6  1120.3   293.7 1111.75   354.5  1089.1
   364.6 1081.59     395 1070.19   445.6 1057.38   526.6 1043.58     557  1042.8
   729.2 1043.58   739.3 1046.04   759.6 1059.21   820.3 1087.77   840.6 1102.19
   891.2 1127.08   911.5 1142.96   972.2 1179.03   992.5 1199.23  1043.1 1232.84
  1063.4 1252.73  1093.8 1270.02  1144.4 1286.12  1276.1  1294.2  1357.1 1308.06
#Mann= 3 , 0 , 0
    10.1      .1       0   526.6    .045       0   729.2      .1       0
Bank Sta=526.6,729.2
XS Rating Curve= 0 ,0
Exp/Cntr=0.3,0.1

Type RM Length L Ch R = 1 ,1041.3  ,1040.2,1041.3,1042.5
XS GIS Cut Line= 3
     1734564.297      223251.846     1733972.606      223874.862
     1733854.268      224184.629
#Sta/Elev= 30
    10.1 1151.74    60.7 1139.74    80.9 1127.95   121.3 1111.75   161.7 1097.62
     182 1086.76   212.3 1075.31   313.4 1044.98   333.6 1042.85   586.3 1042.79
   593.8 1043.01   606.5 1044.98     657 1069.93   677.3 1076.82   697.5 1090.75
   717.7 1099.88   778.3 1122.82   798.6 1133.04   818.8 1137.89   849.1 1148.12
   869.3    1151   889.4 1150.81   989.8 1124.49    1030 1117.07  1040.1 1116.46
  1100.4 1116.92  1130.5 1122.66  1140.6 1121.47  1170.7 1131.58  1190.8 1140.44
#Mann= 3 , 0 , 0
    10.1      .1       0   333.6    .045       0   593.8      .1       0
Bank Sta=333.6,593.8
XS Rating Curve= 0 ,0
Exp/Cntr=0.3,0.1

Chan Stop Cuts=-1
Use User Specified Reach Order=0